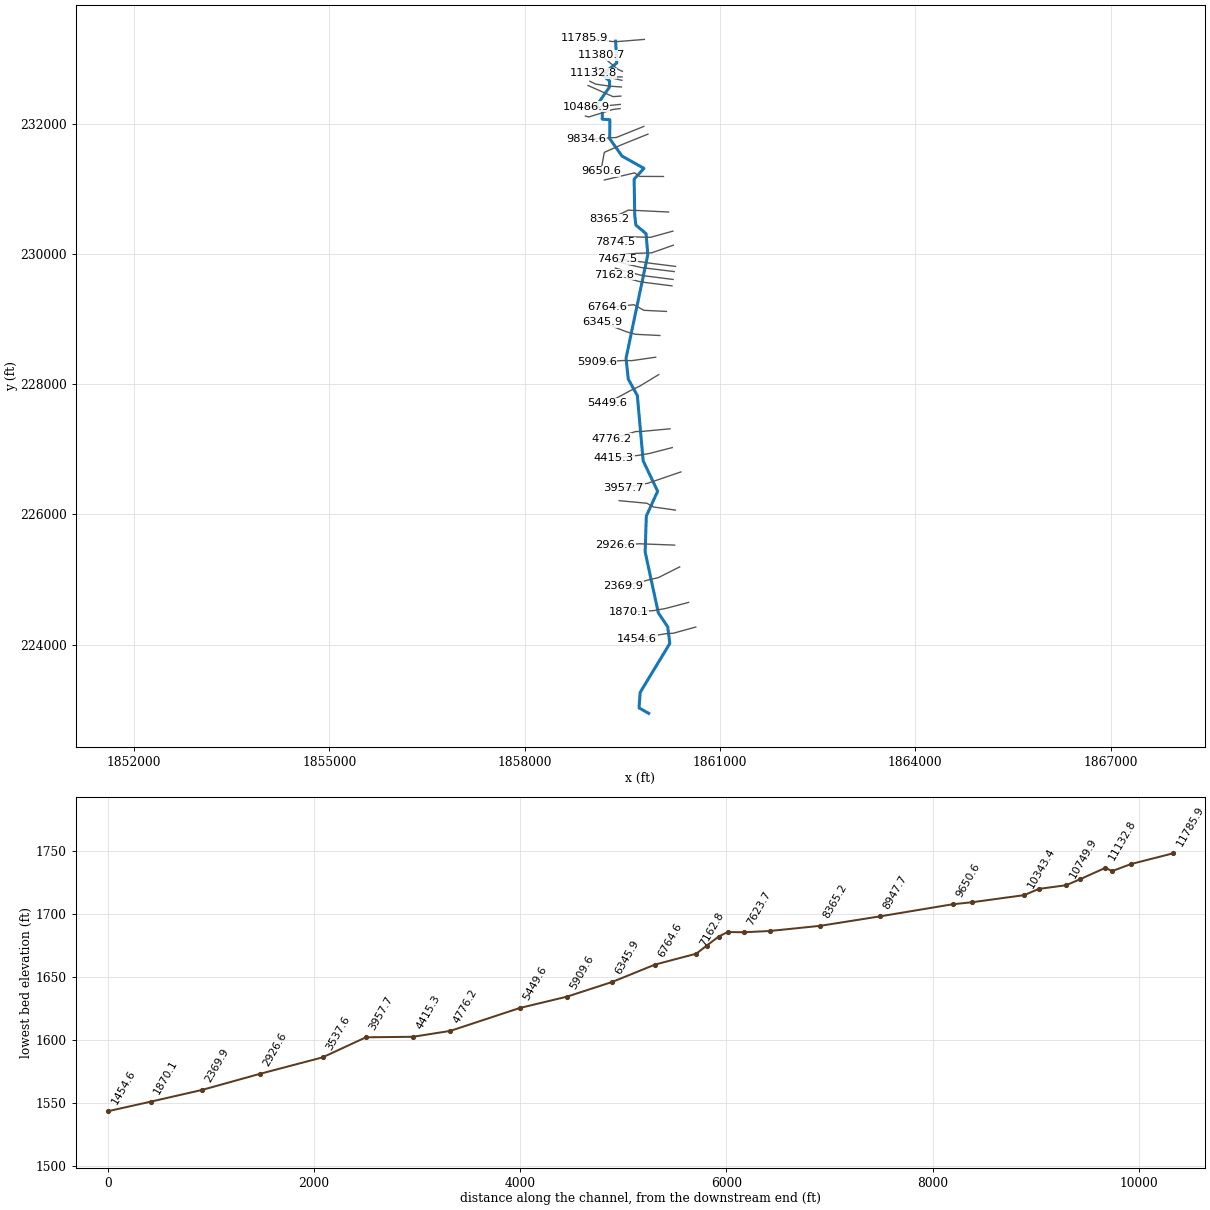
--- CedarCr2.prj (project) ---

Proj Title=CedarCr2
Current Plan=p01
Default Exp/Contr=0,0
English Units
Geom File=g01
Flow File=f01
Plan File=p01
BEGIN DESCRIPTION:
END DESCRIPTION:
DSS Export Rating Curves= 0
DSS Export Rating Curve Sorted= 0
DSS Export Volume Flow Curves= 0
DXF OffsetX= 0
DXF OffsetY= 0
DXF ScaleX= 0
DXF ScaleY= 0

--- CedarCr2.p01 (plan) ---

Plan Title=Floodplain
Program Version=4.00
Geom File=g01
Flow File=f01
K Sum by GR=0
Std Step Tol=0.01
Critical Tol=0.01
Num of Std Step Trials=20
Max Error Tol=0.3
Flow Tol Ratio=0.001
Split Flow NTrial=30
Split Flow Tol=0.02
Split Flow Ratio=0.02
Log Output Level=0
Friction Slope Method=1
Unsteady Friction Slope Method=2
Unsteady Bridges Friction Slope Method=1
Global Log Level=0
CheckData=False
Run HTab=0
Run UNet=0
Run PostProcess=0
UNET Theta=0
UNET Theta Warmup=0
UNET ZTol=0
UNET ZSATol=0
UNET MxIter=0
UNET MaxInSteps=0
UNET DtIC=0
UNET DtMin=0
UNET MaxCRTS=0
UNET WFStab=0
UNET SFStab=0
UNET WFX=0
UNET SFX=0
UNET DSS MLevel=0
UNET DZMax Abort=0
UNET Convert EG Bridges=0
UNET Use Existing IB Tables=0
UNET Froude Limit=0
UNET Froude Power=0
Write IC File=0
Echo Input=False
Echo Output=False
Write Detailed=0

--- CedarCr2.f01 (steady flow) ---

Flow Title=NFF Regression Equation
Program Version=4.00
Number of Profiles=1
Profile Names=P100yr
River Rch & RM=CedarCr2,Main      ,11785.9
560.3101
River Rch & RM=CedarCr2,Main      ,10486.9
596.5677
River Rch & RM=CedarCr2,Main      ,9650.6
630.9534
River Rch & RM=CedarCr2,Main      ,8947.7
688.8150
River Rch & RM=CedarCr2,Main      ,8365.2
702.3507
River Rch & RM=CedarCr2,Main      ,7162.8
766.4467
River Rch & RM=CedarCr2,Main      ,4776.2
837.5506
River Rch & RM=CedarCr2,Main      ,3537.6
914.7905
River Rch & RM=CedarCr2,Main      ,1454.6
945.4939
River Rch & RM=CedarCr2,Main      ,1153
1345.150
River Rch & RM=CedarCr2,Main      ,224.3
1352.024
Boundary for River Rch & Prof#=CedarCr2,Main      ,1
Up Type=0
Dn Type=3
Dn Slope=0.02124

--- CedarCr2.g01 (geometry) ---

Geom Title=USGS 10m DEM
Program Version=4.00

River Reach=CedarCr2        ,Main
Reach XY= 30
     1859397.124      233265.175     1859415.183      232929.423
     1859189.555      232747.966     1859304.783       232653.96
     1859301.185      232556.273     1859094.678      232262.925
     1859195.632      232192.492     1859190.937      232065.712
     1859308.325      232058.669     1859306.547      231766.663
     1859496.146      231499.901     1859831.876       231312.08
     1859681.619      231145.389     1859690.992      230594.278
     1859708.138       230441.14     1859864.745      230309.585
     1859891.861      229987.538     1859557.157      228396.022
     1859591.771      228075.997     1859730.833      227824.592
     1859820.394       226821.94     1860043.062      226355.565
     1859868.921      225973.263      1859851.07      225423.492
     1860053.287      224488.921     1860197.814      224272.737
     1860229.999      224018.296     1859774.555      223267.724
     1859757.146      223029.737     1859905.134      222945.376

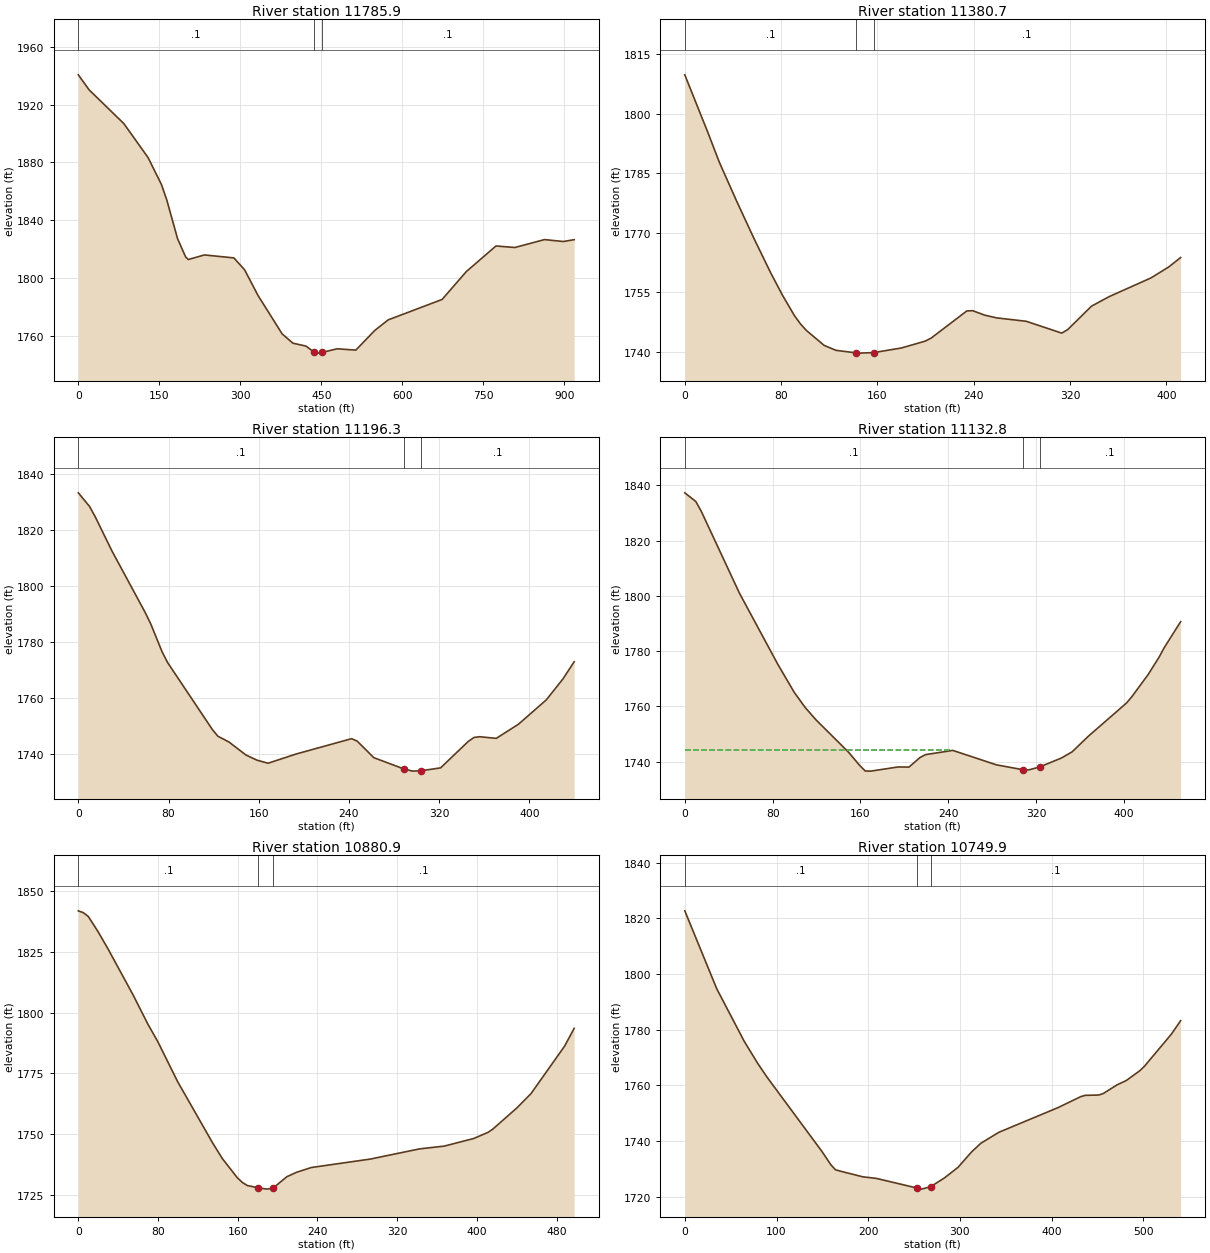
Type RM Length L Ch R = 1 ,11785.9 ,421.1,405.2,389.3
XS GIS Cut Line= 4
       1859839.6      233291.208     1859438.524      233258.784
     1859346.983      233258.784     1858925.422      233307.651
#Sta/Elev= 30
       0 1940.55    19.9 1930.19    84.4 1906.77   129.2 1883.29     154 1864.63
   163.9 1853.89   183.8 1827.19   198.7 1814.62   203.7 1812.77   233.5 1815.96
   288.1  1813.9     308 1805.64   332.8 1787.91   377.6 1761.27   397.4 1754.92
   421.7 1752.88   435.9 1748.93   445.8 1748.03   450.9 1748.48   479.5 1751.04
   513.9  1750.1   548.8 1763.64   573.8 1771.02   673.7 1785.15   718.6 1804.44
   773.5 1822.15   808.5  1821.1   863.4 1826.57   898.3 1825.24   918.3 1826.51
#Mann= 3 , 0 , 0
       0      .1       0   435.9    .045       0   450.9      .1       0
Bank Sta=435.9,450.9
XS Rating Curve= 0 ,0
Exp/Cntr=0.3,0.1

Type RM Length L Ch R = 1 ,11380.7 ,179.5,184.5,189.4
XS GIS Cut Line= 3
     1859501.945      232800.734     1859428.518      232835.361
     1859173.184      233045.461
#Sta/Elev= 30
       0 1809.83    19.1 1795.34    28.6 1787.83      43    1778    57.3 1768.63
    71.6 1759.71    81.2 1754.18      91 1749.09      96    1747   100.9 1745.35
   115.7 1741.56   125.6  1740.3     142 1739.68   145.3  1739.6     157 1739.74
   179.9  1740.9   199.6 1742.62   204.6 1743.39   234.2 1750.24   239.1 1750.31
     249 1749.19   258.8  1748.5   283.5 1747.64   313.1 1744.65   318.1 1745.56
   337.8 1751.46   352.6 1753.88   387.2 1758.58     402 1761.36   411.8 1763.72
#Mann= 3 , 0 , 0
       0      .1       0     142    .045       0     157      .1       0
Bank Sta=142,157
XS Rating Curve= 0 ,0
Exp/Cntr=0.3,0.1

Type RM Length L Ch R = 1 ,11196.3 ,58.2,63.5,68.7
XS GIS Cut Line= 3
     1859496.559      232715.733      1859357.88      232715.733
     1859091.928      232856.973
#Sta/Elev= 30
       0 1833.35     9.9 1828.51    14.9 1824.87    29.7 1812.69    59.4 1790.54
    64.4 1786.39    74.3 1776.57    79.2 1772.73   118.9 1748.81   123.8 1746.42
   133.7 1744.34   148.6 1739.74   158.4 1737.88   168.3 1736.78     193 1740.05
   242.4 1745.55   247.3 1744.69   262.1 1738.76     289 1734.71   296.6 1733.96
     304 1734.09   321.3 1735.12     346 1744.61     351 1745.98   355.9 1746.25
   370.7 1745.66   390.4 1750.71   415.1 1759.41   429.9 1766.91   439.8 1773.02
#Mann= 3 , 0 , 0
       0      .1       0     289    .045       0     304      .1       0
#XS Ineff= 2 , 0
          242.69 1745.33
Permanent Ineff=
       F       F
Bank Sta=289,304
XS Rating Curve= 0 ,0
Exp/Cntr=0.3,0.1

Type RM Length L Ch R = 1 ,11132.8 ,248.1,251.9,275.6
XS GIS Cut Line= 3
     1859493.242      232663.375     1859240.888      232721.702
     1859054.408       232769.94
#Sta/Elev= 30
       0 1837.24      10 1834.12    14.9 1830.65    49.8 1800.94    84.7 1775.25
    99.6 1765.14   109.6 1759.64   119.5 1755.14   149.4 1743.34   159.4  1738.6
   164.4 1736.65   169.4  1736.6   194.2  1738.1   204.2 1738.06   214.2 1741.51
   219.2 1742.56   244.1  1744.1   283.7 1738.89   308.4 1737.07   313.3 1737.05
   323.4 1738.14     343 1741.34   352.8 1743.58   367.7 1749.27   402.2 1761.19
   407.2 1763.52     422 1771.52   431.9 1777.76   436.8 1781.34   451.6 1790.63
#Mann= 3 , 0 , 0
       0      .1       0   308.4    .045       0   323.4      .1       0
#XS Ineff= 2 , 0
          242.25 1744.06
Permanent Ineff=
       F       F
Bank Sta=308.4,323.4
XS Rating Curve= 0 ,0
Exp/Cntr=0.3,0.1

Type RM Length L Ch R = 1 ,10880.9 ,138.8,131.1,124.8
XS GIS Cut Line= 4
     1859486.741      232560.778     1859302.709      232574.104
     1859092.689      232604.226     1859002.162      232648.746
#Sta/Elev= 30
       0 1841.87       5 1841.11      10 1839.55      20 1833.16    29.9 1826.12
    54.9  1807.3    69.8 1795.24    79.8    1788    99.7 1771.54   134.6 1746.47
   144.6 1739.86   159.6    1732   164.6 1730.08   169.6 1728.81   180.6 1727.87
   189.4 1727.33   195.6  1727.8   209.2 1732.42     219 1734.26   233.9 1736.23
   293.1  1739.7   342.4 1743.89   367.1 1745.03   396.7 1748.15   411.1 1750.68
   415.9 1752.02   439.9 1760.66   454.3 1766.64     488 1786.17   497.6 1793.51
#Mann= 3 , 0 , 0
       0      .1       0   180.6    .045       0   195.6      .1       0
Bank Sta=180.6,195.6
XS Rating Curve= 0 ,0
Exp/Cntr=0.3,0.1

Type RM Length L Ch R = 1 ,10749.9 ,255,262.9,271.5
XS GIS Cut Line= 3
     1859477.912      232421.431     1859358.491      232412.196
     1858973.972      232583.354
#Sta/Elev= 30
       0 1822.74    34.9 1794.69    64.9  1775.8    79.8 1767.78    89.8 1762.92
   149.5  1736.3   159.4 1731.44   164.3 1729.69   169.3 1729.22     194 1727.16
   208.9 1726.59   253.3 1723.11   258.4 1722.73   268.3 1723.66   283.2 1726.77
     298 1730.58   312.9 1736.16   322.8  1739.2   342.6 1743.17     407 1752.02
   431.7 1755.96   436.7 1756.43   451.5 1756.55   456.5 1757.11   471.4  1760.2
   481.2 1761.71   496.1 1765.26   501.1 1766.83   530.8  1778.5   540.7 1783.27
#Mann= 3 , 0 , 0
       0      .1       0   253.3    .045       0   268.3      .1       0
Bank Sta=253.3,268.3
XS Rating Curve= 0 ,0
Exp/Cntr=0.3,0.1

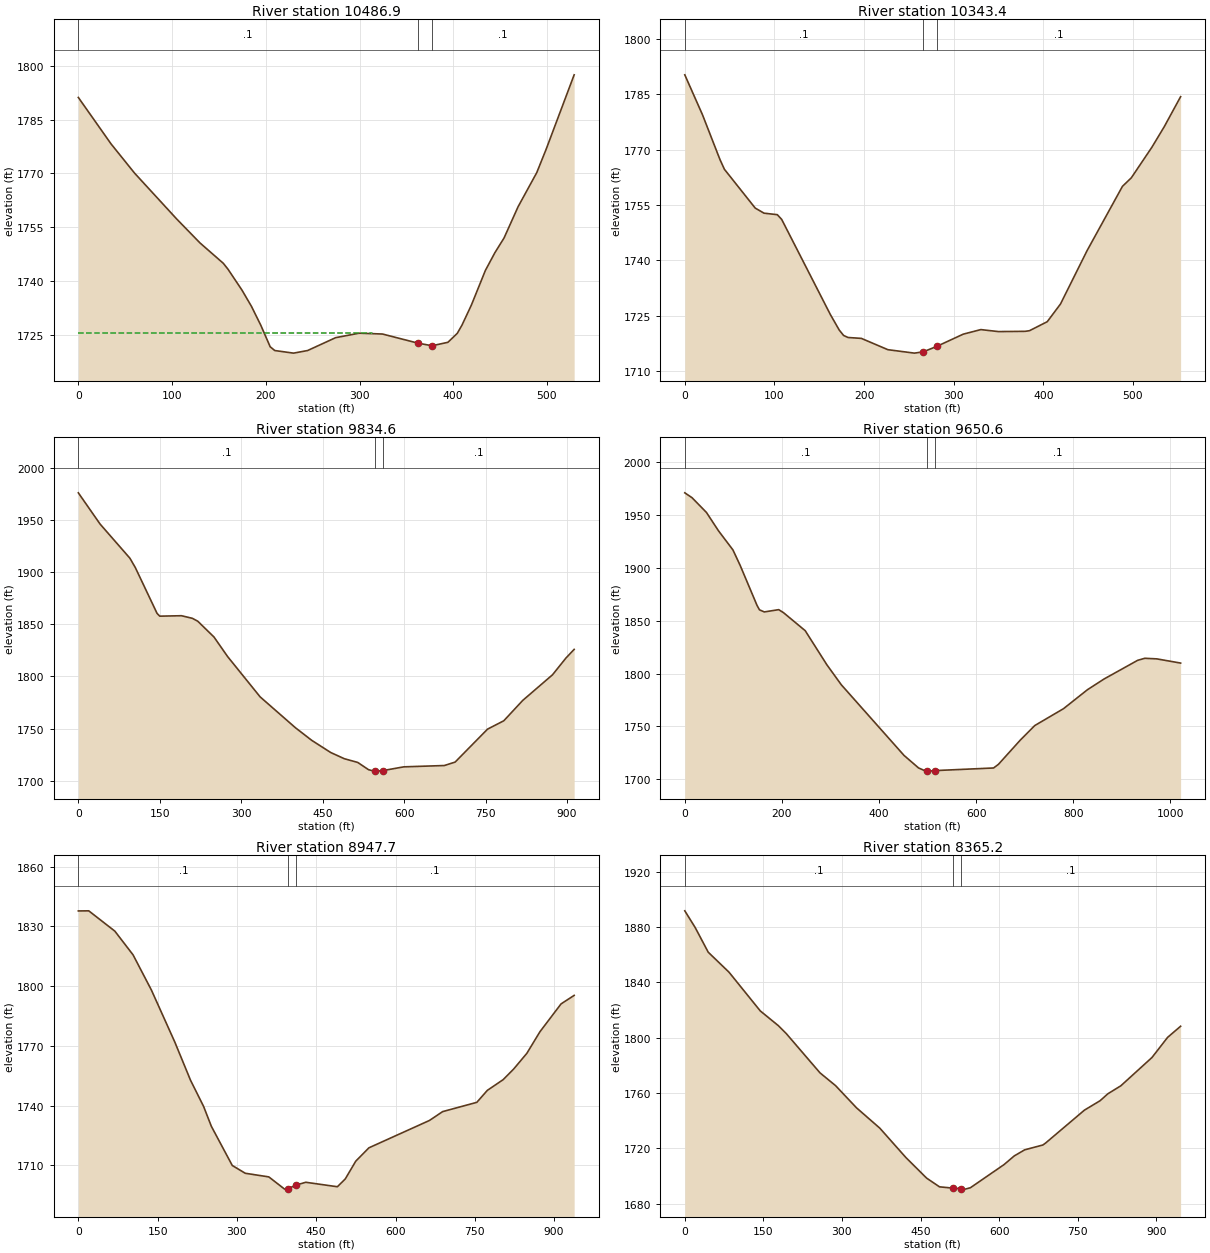
Type RM Length L Ch R = 1 ,10486.9 ,135.2,143.5,151.3
XS GIS Cut Line= 3
     1859469.827      232293.837     1859017.848      232248.568
     1858943.544      232256.628
#Sta/Elev= 30
       0  1791.2    34.9 1778.24    59.9 1770.11   104.8 1757.32   129.8  1750.6
   154.7 1744.91   159.7 1743.26   174.7 1737.39   184.7 1732.91   194.7 1727.62
   204.7 1721.62   209.6 1720.57   229.6 1719.85   244.6 1720.57   274.5 1724.16
   299.5 1725.41   324.5 1725.18   362.4 1722.63   377.4 1721.91   394.3 1722.87
   404.3 1725.37   409.3 1727.65   419.3 1733.23   434.3 1742.93   444.3 1747.82
   454.2 1751.98   469.2 1760.71   489.1 1770.22   499.1 1776.73     529 1797.51
#Mann= 3 , 0 , 0
       0      .1       0   362.4    .045       0   377.4      .1       0
#XS Ineff= 2 , 0
          313.55 1725.33
Permanent Ineff=
       F       F
Bank Sta=362.4,377.4
XS Rating Curve= 0 ,0
Exp/Cntr=0.3,0.1

Type RM Length L Ch R = 1 ,10343.4 ,510.6,508.8,504
XS GIS Cut Line= 4
     1859465.739      232229.306     1859358.426      232216.229
     1858985.903      232100.531     1858932.708      232114.612
#Sta/Elev= 30
       0 1790.22    19.7 1779.43    39.3 1767.25    44.2 1764.65    78.6 1754.14
    88.4 1752.77   103.2 1752.36   108.1 1751.08   162.4 1725.33   172.3 1721.13
   177.2 1719.66   182.2 1719.11     197 1718.87   226.6 1715.81   256.2 1714.88
     266 1715.23     281 1716.69   310.6 1720.01   330.3 1721.25     350 1720.71
   379.7 1720.78   384.6 1720.95   404.4 1723.39   419.2 1728.19   448.8 1742.61
   488.3 1760.03   498.2 1762.34   521.1  1770.6   534.9 1776.16   553.2 1784.31
#Mann= 3 , 0 , 0
       0      .1       0     266    .045       0     281      .1       0
Bank Sta=266,281
XS Rating Curve= 0 ,0
Exp/Cntr=0.3,0.1

Type RM Length L Ch R = 1 ,9834.6  ,176,183.9,191.9
XS GIS Cut Line= 3
     1859829.773      231955.352     1859407.726      231785.625
     1858950.223      231757.255
#Sta/Elev= 30
       0 1975.81      40 1945.94      95 1913.16     105 1904.18     145 1860.33
     150 1857.65     190 1858.07     210 1855.59     220 1852.81   249.9 1837.66
   274.9    1819   334.9 1780.31   399.9 1750.76   429.9 1738.69   464.9 1727.02
   489.8 1721.11   514.7 1717.51   534.6 1710.55   544.6 1709.19   546.2 1709.25
   561.2 1709.72   599.4 1713.28   674.1 1714.55     694 1717.83   753.8 1749.43
   783.7 1757.43   818.6 1776.94   873.4 1801.47   898.3  1817.6   913.3 1825.82
#Mann= 3 , 0 , 0
       0      .1       0   546.2    .045       0   561.2      .1       0
Bank Sta=546.2,561.2
XS Rating Curve= 0 ,0
Exp/Cntr=0.3,0.1

Type RM Length L Ch R = 1 ,9650.6  ,727.3,703,684.1
XS GIS Cut Line= 4
     1859893.517      231836.897     1859493.195       231675.88
     1859223.656      231557.639     1859170.393      231267.085
#Sta/Elev= 30
       0 1971.13    14.9 1966.51    44.6 1952.55    69.4 1935.18    99.2 1917.05
   114.1 1902.36   148.8 1864.53   153.8 1860.36   163.7 1858.37   193.4 1860.52
   203.4 1857.63     248 1840.62   292.6 1808.35   322.4 1789.38   451.4 1722.59
   481.4 1710.68   496.3 1707.65   499.8 1707.68   514.8 1708.14     636 1710.63
     646 1714.09   690.9 1736.98   720.8 1750.81     780 1766.77   829.2  1784.7
   863.7 1794.92   932.6 1812.53   947.4 1814.48     972 1813.93  1021.2 1809.95
#Mann= 3 , 0 , 0
       0      .1       0   499.8    .045       0   514.8      .1       0
Bank Sta=499.8,514.8
XS Rating Curve= 0 ,0
Exp/Cntr=0.3,0.1

Type RM Length L Ch R = 1 ,8947.7  ,571.7,582.4,592.7
XS GIS Cut Line= 4
     1860132.346      231187.098     1859767.143      231188.339
     1859689.192      231242.508     1859224.133      231132.849
#Sta/Elev= 30
       0 1837.71    19.7 1837.77    69.1 1827.57   103.6 1815.64   138.2 1798.02
   182.6 1771.83   212.2 1752.74   236.9 1739.61   251.7 1729.56   291.2 1709.93
   315.8 1706.02   360.3  1704.2   390.2 1698.06     397 1698.35     412  1700.1
   430.2  1701.5     490 1699.26   504.9 1703.16   524.8  1712.1   549.7  1718.8
   664.2 1732.53   689.1 1736.97   753.8 1741.63   773.7 1747.64   803.6 1753.02
   823.5 1758.35   848.4 1766.23   873.2 1777.08   913.1 1791.04   937.9 1795.32
#Mann= 3 , 0 , 0
       0      .1       0     397    .045       0     412      .1       0
#XS Ineff= 2 , 0
                           428.7         1701.32
Permanent Ineff=
       F       F
Bank Sta=397,412
XS Rating Curve= 0 ,0
Exp/Cntr=0.3,0.1

Type RM Length L Ch R = 1 ,8365.2  ,489.3,490.7,491.7
XS GIS Cut Line= 4
     1860211.063      230641.366     1859749.967      230663.826
     1859592.745      230670.432      1859298.12      230527.743
#Sta/Elev= 30
       0 1891.66    19.9 1879.54    44.7 1861.76    84.4 1847.31     144 1819.35
   178.7 1808.62   193.6 1802.97   258.1 1774.54   287.9 1765.28   327.6 1749.33
   372.3 1734.56   421.9 1713.39   461.6 1698.46   486.2 1692.16   511.3 1691.25
   526.3 1690.87   535.4 1690.51   545.2 1691.53   609.2  1708.2   628.9 1714.52
   648.8 1718.92   683.5 1722.41   688.4 1723.73   762.8  1747.6   792.6 1754.38
   807.5 1759.41   832.3  1765.2   891.8 1785.68   921.6 1800.22   946.4 1808.24
#Mann= 3 , 0 , 0
       0      .1       0   511.3    .045       0   526.3      .1       0
Bank Sta=511.3,526.3
XS Rating Curve= 0 ,0
Exp/Cntr=0.3,0.1

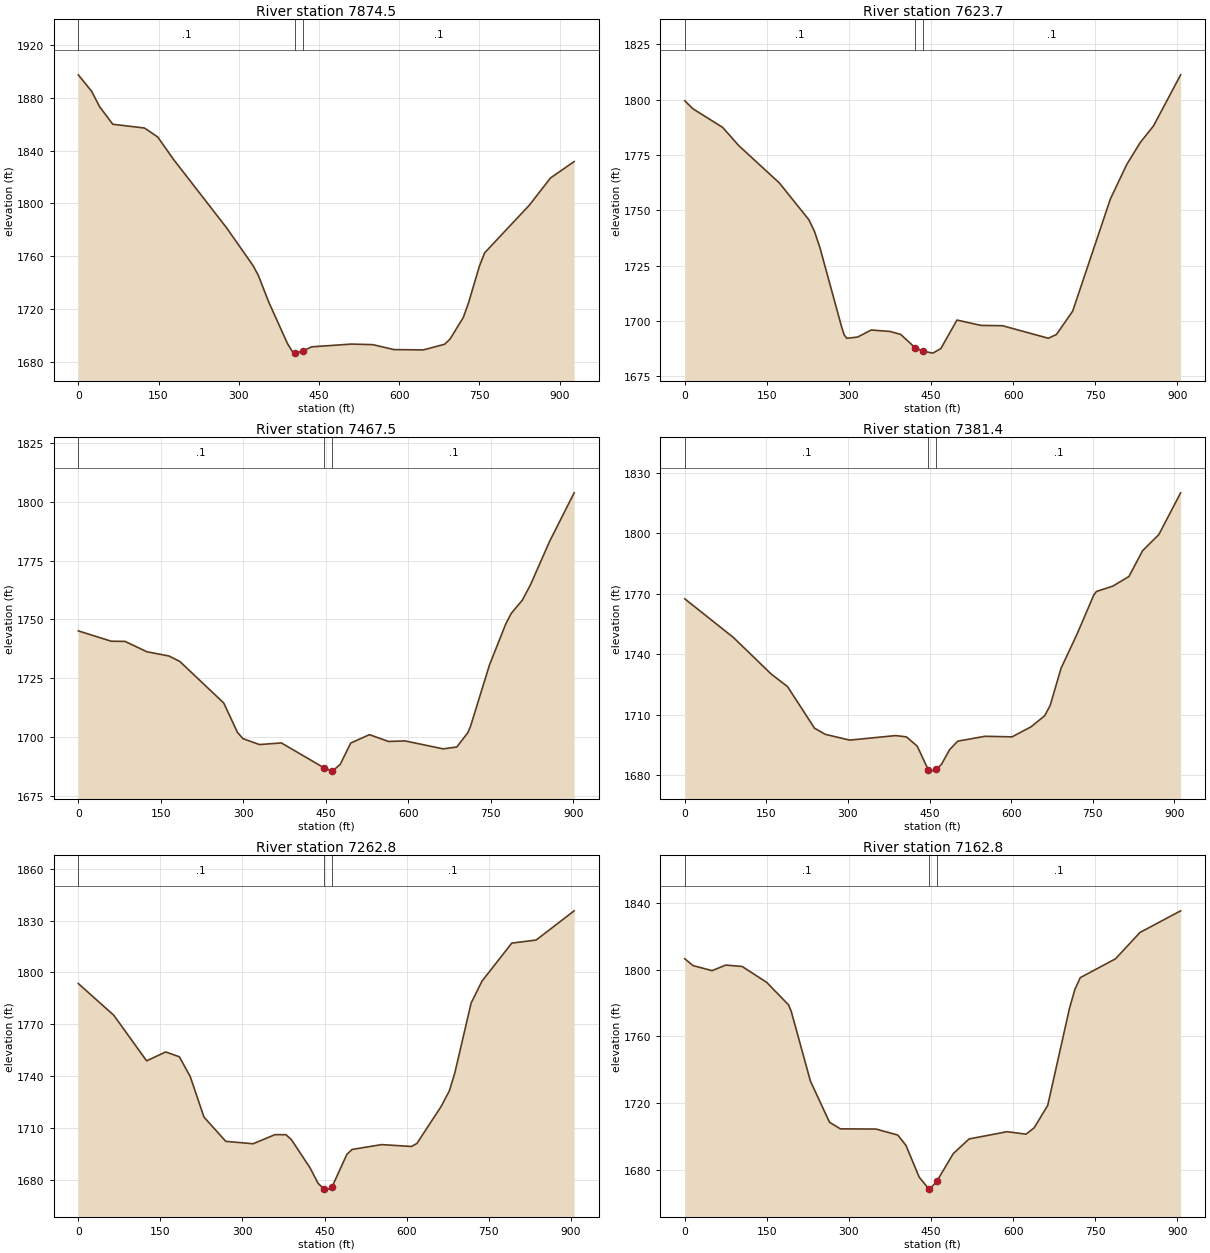
Type RM Length L Ch R = 1 ,7874.5  ,250.2,250.8,251.5
XS GIS Cut Line= 4
     1860277.123      230348.061     1859933.613      230252.935
     1859525.365      230263.505     1859386.639      230178.949
#Sta/Elev= 30
       0 1897.45    24.8    1885    39.6 1873.41    64.4 1859.97   123.8  1857.1
   148.5 1850.32   178.2 1833.21   277.2 1781.47   326.7 1752.83   336.6  1745.4
   356.4 1724.85   391.3 1693.52   401.3 1686.99     406 1686.43   406.2  1686.4
     421 1688.15   436.1 1691.16   510.8 1693.26   550.7 1692.83   590.5 1689.07
   645.3 1688.85   685.1 1693.14   695.1 1697.02     720 1713.46     730 1724.86
   749.9 1752.13   759.8 1762.43   843.6 1798.65     883 1819.21   927.3 1831.67
#Mann= 3 , 0 , 0
       0      .1       0     406    .045       0     421      .1       0
#XS Ineff= 2 , 0
                          517.98         1693.08
Permanent Ineff=
       F       F
Bank Sta=406,421
XS Rating Curve= 0 ,0
Exp/Cntr=0.3,0.1

Type RM Length L Ch R = 1 ,7623.7  ,160.1,156.2,151.8
XS GIS Cut Line= 4
     1860283.885      230132.364     1859953.451      230015.676
     1859713.532      230006.951     1859399.455      229975.326
#Sta/Elev= 30
       0 1799.53    14.8 1795.93    69.1 1787.52    98.7 1779.25   172.8 1762.37
     227 1745.66   236.9 1740.51   246.8 1733.25   286.3 1697.55   291.2  1693.7
   296.1  1692.1   315.9 1692.66   340.6 1695.84   374.9 1695.21   394.5 1693.87
   421.1 1687.81   436.1 1686.23   453.3 1685.39     468 1687.46   497.4 1700.34
   541.5 1697.93   580.7 1697.79   664.5 1692.11   679.3 1693.84   708.9 1704.37
   777.9 1755.18   807.5 1770.62   832.2  1780.6   856.8 1788.24   906.2 1811.28
#Mann= 3 , 0 , 0
       0      .1       0   421.1    .045       0   436.1      .1       0
Bank Sta=421.1,436.1
XS Rating Curve= 0 ,0
Exp/Cntr=0.3,0.1

Type RM Length L Ch R = 1 ,7467.5  ,85.2,86.1,87
XS GIS Cut Line= 4
     1860317.559      229806.662     1859911.565      229857.838
     1859807.507      229874.896     1859422.879      229918.912
#Sta/Elev= 30
       0 1745.13    59.9 1740.74    84.8 1740.67   124.8 1736.26   164.7 1734.48
   184.6 1732.16   264.5  1714.5   289.4 1702.05   299.4 1699.39   329.4 1696.87
   369.3 1697.56   447.1 1686.96   461.9 1685.59   462.1  1685.6   476.3 1688.46
   495.5 1697.52   529.5 1701.07   564.3 1698.18   594.1 1698.42   663.6 1695.04
   688.4 1695.85   708.2 1701.85   713.2 1704.53   747.9 1730.74   777.7 1748.24
   787.6 1752.64   807.5 1758.16   822.4 1764.71   857.1 1783.11   901.8 1803.74
#Mann= 3 , 0 , 0
       0      .1       0   447.1    .045       0   462.1      .1       0
Bank Sta=447.1,462.1
XS Rating Curve= 0 ,0
Exp/Cntr=0.3,0.1

Type RM Length L Ch R = 1 ,7381.4  ,119.6,118.6,117.7
XS GIS Cut Line= 3
     1860297.379      229727.242     1859789.222      229789.352
     1859400.459      229882.976
#Sta/Elev= 30
       0 1767.52    89.5 1748.32     159 1730.17   188.9 1723.98   238.6 1703.32
   258.4 1700.28   303.2 1697.41   387.7 1699.66   407.6 1699.01   427.4 1694.44
   447.8 1682.66   452.3 1682.02   462.8 1682.87   472.2  1685.5   487.1 1692.74
     502 1696.89   551.9 1699.31   601.9 1699.03   636.9 1704.05   661.9 1709.53
   671.9 1714.62   691.9 1733.06   721.9 1750.36   751.9 1769.29   756.9 1771.16
   786.8 1773.79   816.8 1778.61   841.8  1791.4   871.8 1799.44   911.8 1820.13
#Mann= 3 , 0 , 0
       0      .1       0   447.8    .045       0   462.8      .1       0
Bank Sta=447.8,462.8
XS Rating Curve= 0 ,0
Exp/Cntr=0.3,0.1

Type RM Length L Ch R = 1 ,7262.8  ,99.9,99.9,99.9
XS GIS Cut Line= 4
     1860280.524      229606.335     1859874.529      229657.511
     1859770.472      229674.569     1859393.477      229780.332
#Sta/Elev= 30
       0 1793.57    64.9 1775.21   124.8 1748.88   159.7 1754.03   184.6 1751.25
   204.6 1739.76   229.6 1716.38   269.5 1702.34   319.4 1700.96   359.3  1706.2
   379.3 1706.19   389.2 1703.45   423.6 1686.98     438 1678.15   448.5 1674.93
   457.1 1674.72   463.5 1675.85   490.7 1694.76   500.3 1697.66   554.3 1700.46
   608.8 1699.38   618.7 1701.09   663.3 1722.62   678.2  1731.6   688.1 1741.91
   717.9 1782.29   737.7 1794.94   792.2 1816.94   836.8 1818.73   906.2 1835.61
#Mann= 3 , 0 , 0
       0      .1       0   448.5    .045       0   463.5      .1       0
Bank Sta=448.5,463.5
XS Rating Curve= 0 ,0
Exp/Cntr=0.3,0.1

Type RM Length L Ch R = 1 ,7162.8  ,406.1,398.2,390.3
XS GIS Cut Line= 4
      1860263.45      229507.886     1859857.456      229559.061
     1859753.399       229576.12     1859376.404      229681.883
#Sta/Elev= 30
       0 1806.51      15 1802.42    49.9 1799.37    74.8 1802.72   104.8 1801.89
   149.7 1792.35   189.6 1778.86   194.6 1774.91   229.6 1733.16   264.5 1708.46
   284.4 1704.52   349.3  1704.4   389.2 1700.81   404.2 1694.62   428.4 1675.56
   445.5 1668.71   447.6 1668.37   460.5 1673.02   490.7 1689.68   519.6 1698.45
     589 1702.81   623.7 1701.33   638.6 1705.17   663.3 1718.57     703 1776.64
   712.9 1788.09   722.8 1795.18   787.2 1806.48   831.9 1822.27   906.2 1835.25
#Mann= 3 , 0 , 0
       0      .1       0   445.5    .045       0   460.5      .1       0
Bank Sta=445.5,460.5
XS Rating Curve= 0 ,0
Exp/Cntr=0.3,0.1

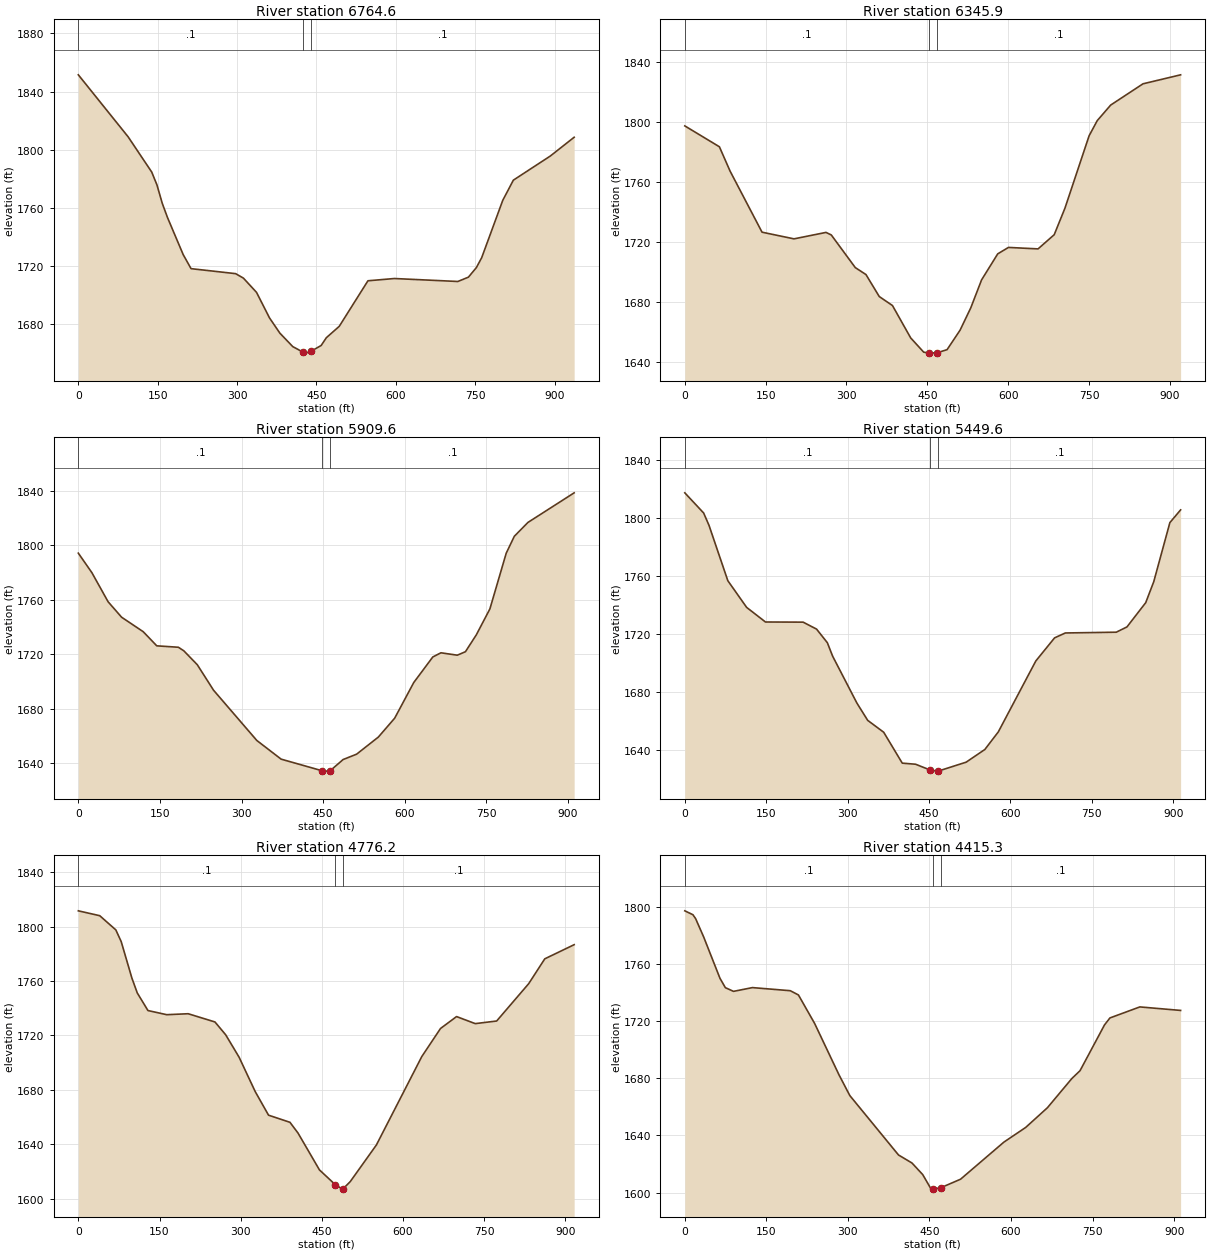
Type RM Length L Ch R = 1 ,6764.6  ,413.3,418.8,424.2
XS GIS Cut Line= 4
     1860178.157      229115.538     1859831.868      229132.597
     1859678.341       229217.89     1859265.523      229178.655
#Sta/Elev= 30
       0 1851.52    94.1 1808.82   138.7 1784.53   148.6 1775.66   158.5 1763.12
   168.4 1753.29   198.1 1727.71     213 1717.98   297.2 1714.54     312 1711.44
   336.8 1701.62   361.3 1684.03   380.9 1673.54   405.2 1664.28   424.7 1660.45
   429.6 1659.78   439.7 1661.05   458.9 1665.04   468.7  1670.4   493.1 1678.25
   547.3 1709.62   597.3 1711.18   717.2 1709.14   737.2 1712.12   752.2  1718.7
   762.2 1725.48   802.1 1765.06   822.1 1778.94     892 1795.59     937 1808.51
#Mann= 3 , 0 , 0
       0      .1       0   424.7    .045       0   439.7      .1       0
Bank Sta=424.7,439.7
XS Rating Curve= 0 ,0
Exp/Cntr=0.3,0.1

Type RM Length L Ch R = 1 ,6345.9  ,430.5,436.2,442
XS GIS Cut Line= 4
     1860077.096      228745.868      1859701.92      228764.589
     1859571.726      228800.564     1859189.408       228946.45
#Sta/Elev= 30
       0 1797.63    64.2 1783.68      84 1767.44   143.3 1726.65   202.6 1722.19
     262  1726.5   271.8 1724.79   316.3 1703.01   336.1 1698.36   360.8 1683.67
   385.3 1677.67   419.1 1656.05   443.2 1646.55   452.8 1645.89   453.6 1645.89
   468.6 1646.18   486.6 1648.21   510.7  1661.2   530.7 1676.22   550.6 1694.79
   580.6 1712.18   600.5 1716.47   655.4 1715.49   685.4 1724.97   705.3  1742.7
   750.2  1791.1   765.2 1801.13   790.2 1811.54   850.1 1825.72   919.9 1831.72
#Mann= 3 , 0 , 0
       0      .1       0   453.6    .045       0   468.6      .1       0
Bank Sta=453.6,468.6
XS Rating Curve= 0 ,0
Exp/Cntr=0.3,0.1

Type RM Length L Ch R = 1 ,5909.6  ,449.7,460,470.4
XS GIS Cut Line= 4
     1860012.885       228412.97     1859648.815      228360.305
     1859510.056      228362.018     1859106.039      228335.574
#Sta/Elev= 30
       0 1794.35    24.9 1780.05    54.7 1758.68    79.5 1747.33   119.3 1736.67
   144.2 1726.29   183.9 1725.25   193.9 1722.65   218.7 1712.42   248.6 1693.69
   328.1  1656.8   372.8 1643.07   448.5  1634.5   457.1 1634.27   463.5 1634.73
   486.8  1642.8   511.6 1646.72   551.6  1659.3   581.6 1673.17   616.6 1699.32
   651.6 1718.09   666.6 1721.18   696.6 1719.42   711.6 1721.96   731.6 1734.33
   756.6 1753.42   786.6 1794.32   801.5 1806.75   826.5 1816.91   911.5 1838.67
#Mann= 3 , 0 , 0
       0      .1       0   448.5    .045       0   463.5      .1       0
Bank Sta=448.5,463.5
XS Rating Curve= 0 ,0
Exp/Cntr=0.3,0.1

Type RM Length L Ch R = 1 ,5449.6  ,683.5,673.4,663.4
XS GIS Cut Line= 4
       1860060.2      228146.341      1859763.59      227966.298
     1859626.545      227901.201     1859261.013       227704.58
#Sta/Elev= 30
       0 1817.55    34.7 1803.62    44.6  1795.1    79.3 1756.82     114 1738.37
   148.7 1728.28   218.1 1728.18   242.9 1723.35   262.7 1713.98   272.6 1704.56
   317.2 1672.25   337.1  1660.3   366.6 1652.08   400.8 1630.73   425.3 1629.99
   452.1    1626   464.4 1625.22   467.1 1625.25   518.5  1631.4     553 1640.18
   577.8 1652.33   646.9 1701.33   681.5 1717.31   701.3  1720.7   795.2 1721.23
   814.9 1724.88   849.5 1741.66   864.3 1756.16     894 1796.98   913.8 1805.76
#Mann= 3 , 0 , 0
       0      .1       0   452.1    .045       0   467.1      .1       0
Bank Sta=452.1,467.1
XS Rating Curve= 0 ,0
Exp/Cntr=0.3,0.1

Type RM Length L Ch R = 1 ,4776.2  ,357,360.9,364.7
XS GIS Cut Line= 4
     1860232.972      227313.618     1859789.287      227272.504
     1859708.772      227272.504     1859335.323      227159.442
#Sta/Elev= 30
       0 1811.63    39.6 1808.04    69.3 1797.61    79.2 1789.04      99 1762.18
   108.9 1751.28   128.7 1738.32   163.4 1735.28     203 1735.98   252.5 1729.93
   272.3 1720.52   297.1 1704.03   326.8 1678.83   351.5 1661.41   391.1 1656.17
     406 1648.27   445.6 1621.19   474.8 1610.34   488.2 1607.05   489.8  1607.5
   502.4 1612.52   550.8 1639.49   634.8 1704.54   669.3 1725.12     699  1733.9
   733.5 1728.71   773.1 1730.64   832.3 1758.08     862 1776.34   916.3 1786.74
#Mann= 3 , 0 , 0
       0      .1       0   474.8    .045       0   489.8      .1       0
Bank Sta=474.8,489.8
XS Rating Curve= 0 ,0
Exp/Cntr=0.3,0.1

Type RM Length L Ch R = 1 ,4415.3  ,455,457.6,460.3
XS GIS Cut Line= 4
     1860267.817      227025.341     1859916.054      226935.029
     1859744.747      226905.907     1859372.168      226863.756
#Sta/Elev= 30
       0 1797.03    14.9 1794.32    19.9 1791.59    34.8 1778.68    64.7 1749.83
    74.6 1743.29    89.6  1740.7   124.4 1743.33     194 1741.16     209 1738.19
   238.8 1718.25   283.6 1682.32   303.5 1667.82     393 1626.28   417.8 1620.66
   437.6 1612.54   452.5 1602.75   456.7 1602.44   457.5 1602.38   471.7  1603.5
   507.2 1609.32   586.9 1635.27   626.9 1645.51   666.9  1659.3   711.9 1679.76
   726.9 1685.21   771.9 1717.22   781.9 1722.11   836.9 1729.82   911.9 1727.37
#Mann= 3 , 0 , 0
       0      .1       0   456.7    .045       0   471.7      .1       0
Bank Sta=456.7,471.7
XS Rating Curve= 0 ,0
Exp/Cntr=0.3,0.1

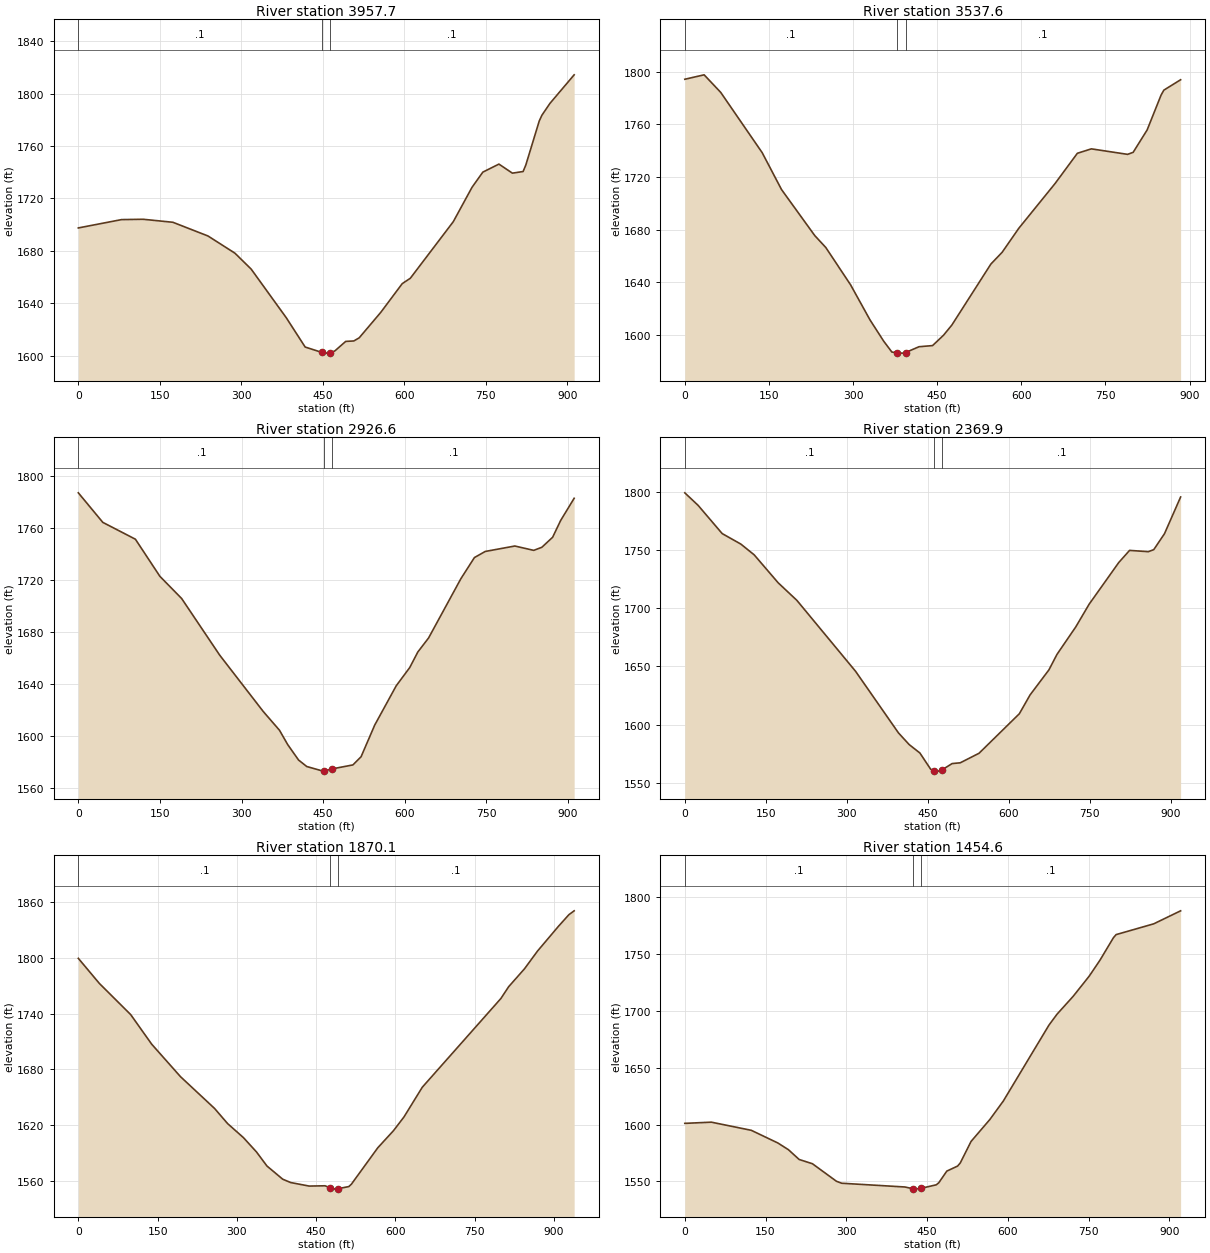
Type RM Length L Ch R = 1 ,3957.7  ,439.4,420,400.7
XS GIS Cut Line= 3
     1860400.048      226651.882     1859892.007      226477.974
     1859522.034      226411.962
#Sta/Elev= 30
       0 1697.52    79.6 1703.88   119.3 1704.13     174 1701.85   238.7 1691.38
   288.4 1678.22   318.2 1666.09   382.8 1628.98   417.6 1606.61   448.7 1602.46
   457.4 1601.96   463.7 1602.13   472.4  1603.7   492.2  1610.9   507.2 1611.25
   517.1 1613.65   556.8 1633.08   596.3 1655.01   611.2 1659.11   690.3  1702.3
   724.9 1728.61   744.7 1740.12   774.3 1746.24   799.1 1739.34   818.8 1740.58
   823.8 1745.53   848.5 1779.12   853.5 1783.58   868.3 1792.63   912.8 1814.39
#Mann= 3 , 0 , 0
       0      .1       0   448.7    .045       0   463.7      .1       0
Bank Sta=448.7,463.7
XS Rating Curve= 0 ,0
Exp/Cntr=0.3,0.1

Type RM Length L Ch R = 1 ,3537.6  ,600,611,622
XS GIS Cut Line= 4
     1860315.934      226065.932      1859979.17      226113.476
      1859878.14      226170.924     1859452.232      226210.543
#Sta/Elev= 30
       0 1794.29    34.5 1797.66    64.1 1784.28     138 1738.46   172.5  1710.4
   231.7 1675.44   251.4 1666.37   295.7 1637.91   330.2 1611.33   354.6 1595.15
   369.2 1586.86   378.6  1586.2   388.5 1586.03   393.6 1586.46   417.6  1590.9
   441.8 1591.76   461.3 1599.63   476.2 1607.39   545.8 1653.78   565.8 1662.68
   595.6 1680.99   660.2 1714.99     700    1738   724.9 1741.36   789.6 1737.18
   799.5 1738.74   824.4 1755.74   849.3  1782.3   854.2 1786.01   884.1 1793.92
#Mann= 3 , 0 , 0
       0      .1       0   378.6    .045       0   393.6      .1       0
Bank Sta=378.6,393.6
XS Rating Curve= 0 ,0
Exp/Cntr=0.3,0.1

Type RM Length L Ch R = 1 ,2926.6  ,550.5,556.7,563
XS GIS Cut Line= 3
     1860303.602      225528.477     1859759.282      225548.899
     1859393.621      225522.516
#Sta/Elev= 30
       0 1787.18      45 1764.42   104.9 1751.46   149.9 1722.88   189.9 1705.79
   259.9 1662.14   339.8 1618.83   369.8 1604.31   384.8 1593.32   404.8 1581.41
   419.8 1576.43   449.8 1572.87   451.9 1572.99   466.9 1574.63   504.7 1577.66
   519.7 1583.97   544.7 1608.29   584.3 1638.61   609.1 1652.62     624 1664.62
   643.8 1675.45   703.2 1721.12     728 1737.32   747.8 1742.02   802.3 1746.22
     837 1742.87   851.9 1745.24   871.7 1752.94   886.5 1765.89   911.3 1782.98
#Mann= 3 , 0 , 0
       0      .1       0   451.9    .045       0   466.9      .1       0
Bank Sta=451.9,466.9
XS Rating Curve= 0 ,0
Exp/Cntr=0.3,0.1

Type RM Length L Ch R = 1 ,2369.9  ,501.1,499.8,498.5
XS GIS Cut Line= 3
     1860381.504      225193.905     1860054.446      225029.886
     1859516.986      224901.089
#Sta/Elev= 30
       0 1798.96    24.7  1788.2    69.2 1764.02   103.8    1755   128.6 1745.74
     173 1721.77   207.7 1706.68   316.4 1645.84   395.8 1593.03   415.7 1582.98
   435.6 1575.73   455.5 1561.85   461.7 1560.59   470.4  1560.2   476.7 1561.35
   495.3 1566.69   510.3 1567.33   545.1 1575.52   619.8 1609.42   639.7 1625.59
   674.6 1647.07   689.5 1660.33   724.4 1683.97   749.3 1703.55     804 1739.16
     824 1749.57   858.8 1748.47   868.8 1750.19   888.7 1763.88   918.6 1795.38
#Mann= 3 , 0 , 0
       0      .1       0   461.7    .045       0   476.7      .1       0
Bank Sta=461.7,476.7
XS Rating Curve= 0 ,0
Exp/Cntr=0.3,0.1

Type RM Length L Ch R = 1 ,1870.1  ,418,415.5,413
XS GIS Cut Line= 4
     1860519.133      224648.888     1860159.438      224554.453
     1859977.189      224522.758     1859596.471      224497.518
#Sta/Elev= 30
       0 1799.71    39.7 1772.72    99.2 1738.98   138.8 1707.17   193.4 1672.08
   257.8 1637.86   282.6 1621.47   312.4 1606.43   337.2 1590.91     357 1575.76
   386.9 1561.51   401.9 1557.94   436.9 1554.13   466.9 1554.44   476.9  1552.3
   486.9 1550.84   491.9 1551.38   511.9 1553.58   516.9 1556.24   566.8 1595.46
   596.5 1613.89   616.3 1628.66     651 1660.72   799.7 1756.38   814.5 1769.16
   844.3 1788.35     869 1807.52   908.7 1834.26   928.5 1846.82   938.4 1850.95
#Mann= 3 , 0 , 0
       0      .1       0   476.9    .045       0   491.9      .1       0
Bank Sta=476.9,491.9
XS Rating Curve= 0 ,0
Exp/Cntr=0.3,0.1

Type RM Length L Ch R = 1 ,1454.6  ,314.7,301.6,288.6
XS GIS Cut Line= 4
     1860628.927      224271.175      1860286.22      224176.088
     1860165.381      224168.164     1859727.586      224092.888
#Sta/Elev= 30
       0 1601.06    49.4  1602.1   123.5 1594.95   172.9  1583.8   192.6 1577.87
   212.4 1569.31   237.1 1565.56   281.6 1550.18   291.4 1548.42   408.9 1545.12
   423.3 1543.64   428.3 1543.24   438.3 1543.89   467.1 1547.03   471.9 1548.92
   486.7 1559.08   506.7 1563.51   511.7 1566.25   531.7 1585.14   566.6 1604.42
   591.6 1620.65   676.4  1687.4   691.4 1697.01   721.3 1712.68   751.3 1730.54
   771.2  1744.5   796.2 1764.28   801.2    1767   871.1 1776.47     921  1787.9
#Mann= 3 , 0 , 0
       0      .1       0   423.3    .045       0   438.3      .1       0
Bank Sta=423.3,438.3
XS Rating Curve= 0 ,0
Exp/Cntr=0.3,0.1