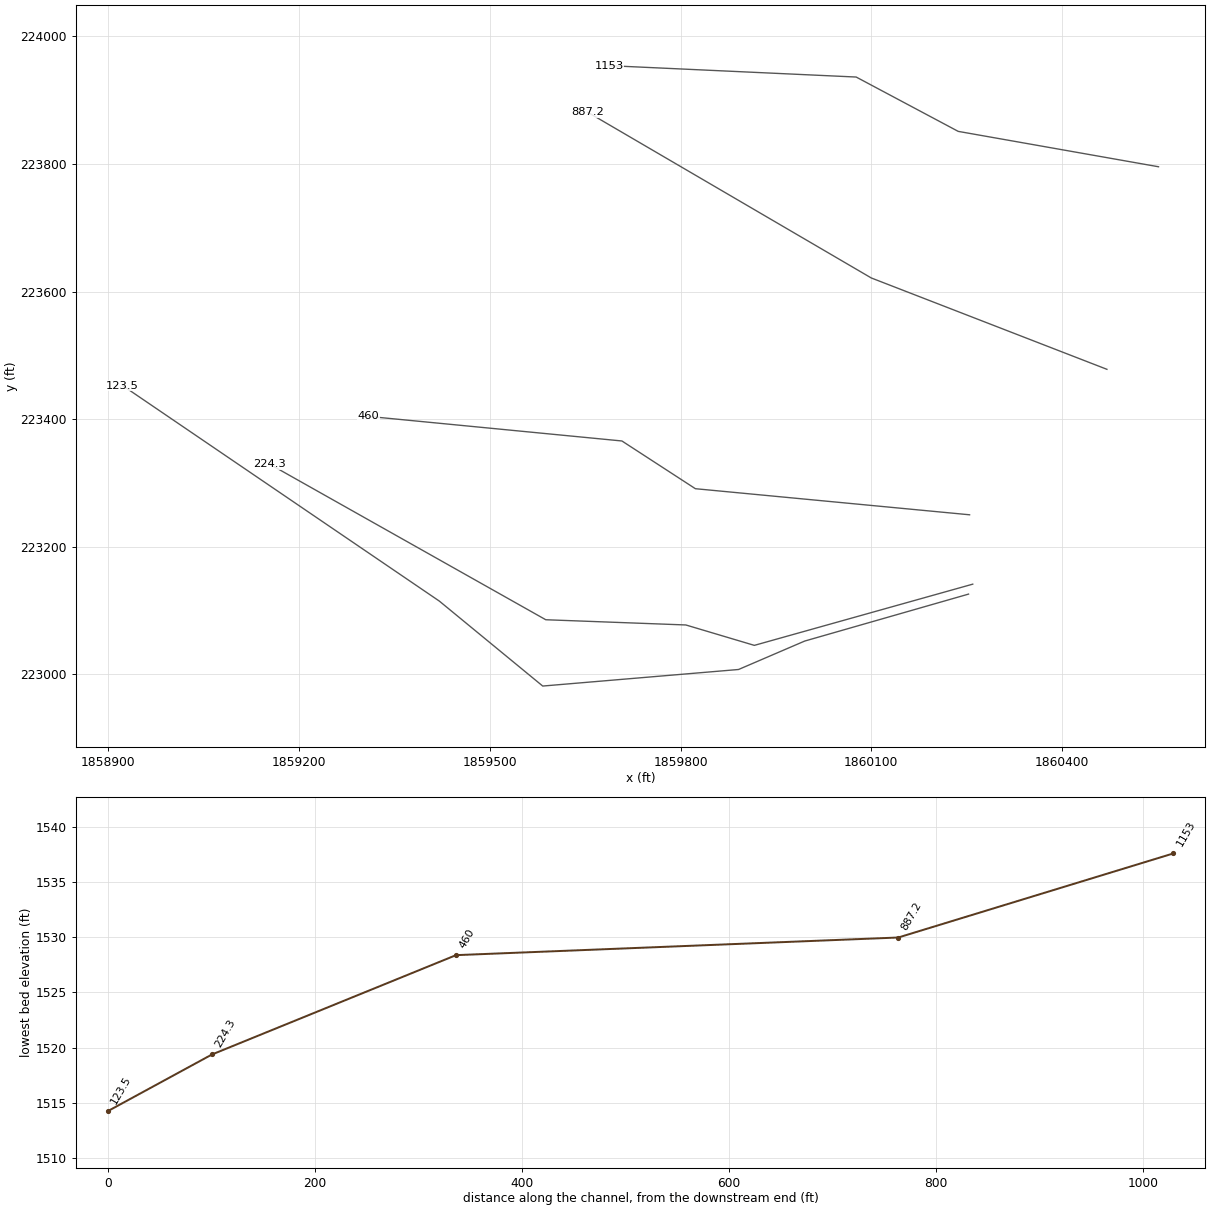
HEC-RAS study CedarCr2.prj: CedarCr2

--- CedarCr2.g01 (geometry) --- (continued)

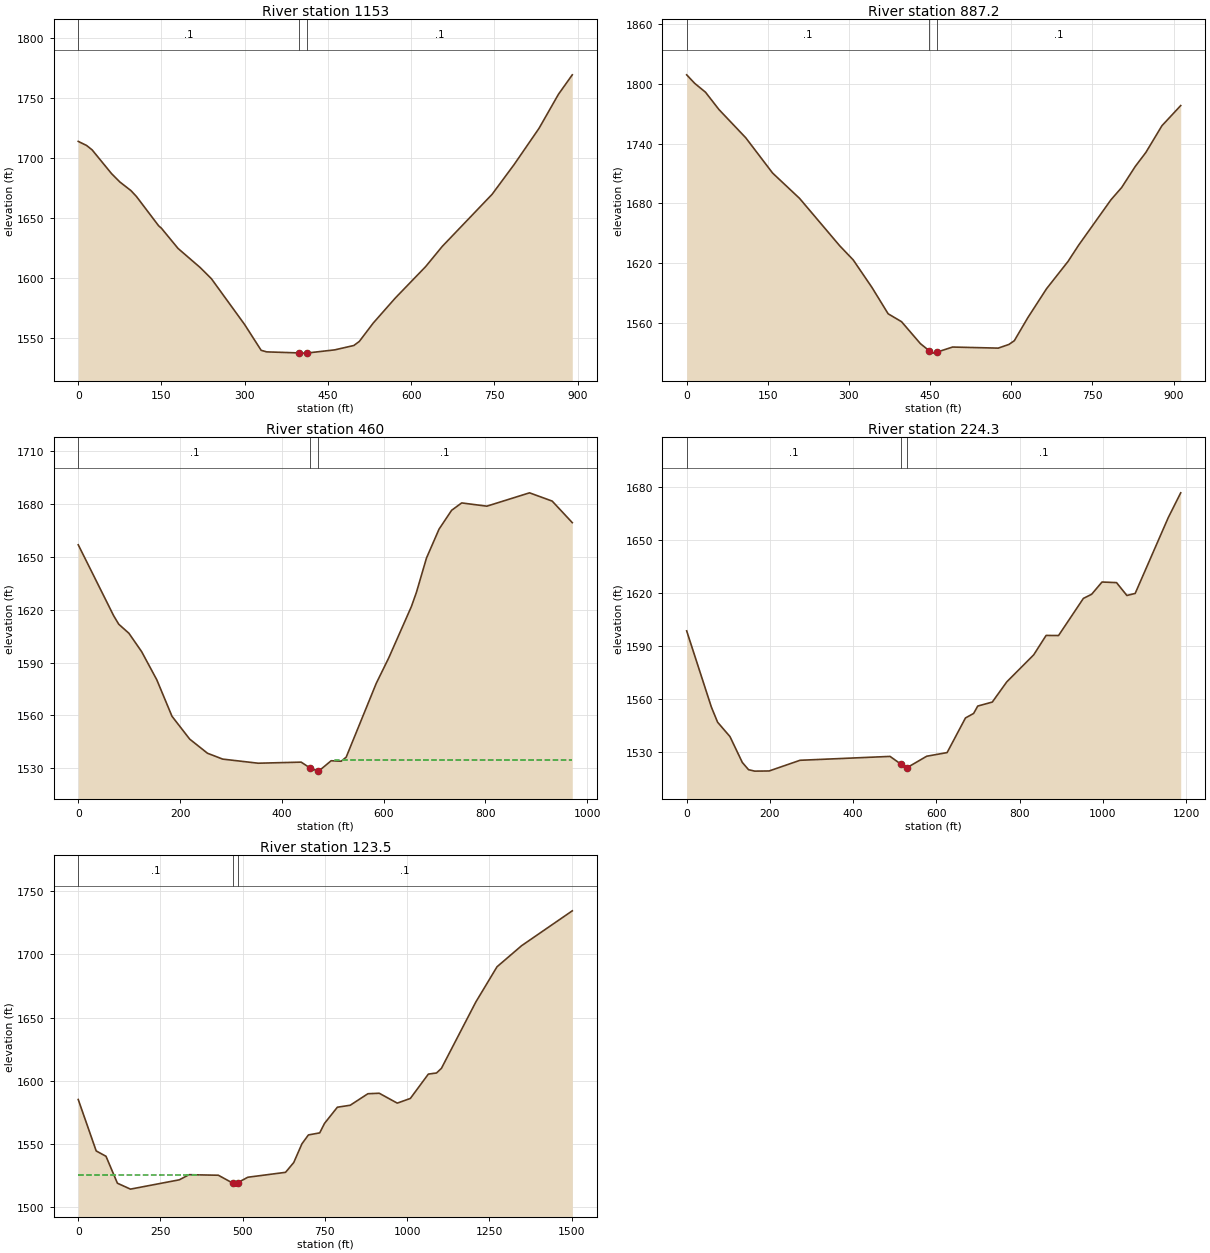
Type RM Length L Ch R = 1 ,1153    ,266.6,265.8,265
XS GIS Cut Line= 4
     1860551.669      223795.742     1860236.696      223851.209
     1860076.237      223936.391     1859687.967       223954.22
#Sta/Elev= 30
       0 1713.85      15 1710.47      25  1706.8      60 1687.03      75 1680.06
      95 1672.88   104.9 1667.98   144.9 1643.58   149.9 1641.57   179.9 1624.72
   219.9 1608.78   239.9 1599.58   299.8 1561.42   329.6 1539.95   339.5 1538.66
     398 1537.78   403.3 1537.61     413 1537.73   462.2 1540.33   496.6 1543.96
   506.5 1547.37   531.4 1562.56   571.2 1583.42   626.1 1609.69     656 1626.49
   745.7  1669.8   785.5 1694.65   830.4  1724.8   865.2 1753.01   890.2 1769.26
#Mann= 3 , 0 , 0
       0      .1       0     398    .045       0     413      .1       0
Bank Sta=398,413
XS Rating Curve= 0 ,0
Exp/Cntr=0.3,0.1

Type RM Length L Ch R = 1 ,887.2   ,428.2,427.1,426
XS GIS Cut Line= 3
     1860470.547      223478.226     1860100.009      223621.417
     1859654.144      223881.169
#Sta/Elev= 30
       0 1808.94    14.9 1800.37    34.8 1791.52    59.6 1774.19   109.2 1745.85
   158.9 1710.45   208.6 1685.13     283 1637.51   307.9 1623.38   342.6 1595.73
   372.4 1569.42   397.2 1561.48     432 1539.51   448.3 1532.36   456.8 1529.98
   463.3 1531.09   491.5 1536.07   575.9    1535   595.7  1538.7   605.6 1542.41
   630.4 1565.34   665.2 1594.53   704.9 1621.88   724.7 1638.34   784.2 1683.63
   804.1 1696.03   828.9 1716.89   848.8 1731.15   878.5 1757.93   913.2 1778.13
#Mann= 3 , 0 , 0
       0      .1       0   448.3    .045       0   463.3      .1       0
Bank Sta=448.3,463.3
XS Rating Curve= 0 ,0
Exp/Cntr=0.3,0.1

Type RM Length L Ch R = 1 ,460     ,223.6,235.7,247.9
XS GIS Cut Line= 4
     1860254.583      223250.186     1859823.404      223291.078
     1859707.884      223365.891     1859309.693      223404.398
#Sta/Elev= 30
       0  1656.8    69.7  1616.5    79.6 1611.73    99.6 1606.59   124.5 1596.21
   154.3 1580.23   184.2 1559.51     219 1546.55   253.9 1538.54   283.8  1535.2
   353.5 1532.87     438 1533.48   456.1 1530.07   471.1 1528.46   472.4 1528.38
     497 1534.27   516.7    1534   526.5 1536.29   585.6 1578.19   610.2 1592.66
   654.7 1621.79   664.6 1629.87   684.3 1649.28     709 1665.68   733.7 1676.37
   753.5 1680.55   802.9  1678.7   886.8 1686.28   931.3 1681.59   970.8 1669.36
#Mann= 3 , 0 , 0
       0      .1       0   456.1    .045       0   471.1      .1       0
#XS Ineff= 2 , 0
                             505         1534.68
Permanent Ineff=
       F       F
Bank Sta=456.1,471.1
XS Rating Curve= 0 ,0
Exp/Cntr=0.3,0.1

Type RM Length L Ch R = 1 ,224.3   ,106.2,100.8,91.9
XS GIS Cut Line= 5
     1860259.539      223141.453     1859916.121      223045.498
     1859808.382      223077.483     1859588.128      223085.671
     1859154.296       223329.33
#Sta/Elev= 30
       0 1598.64    59.4 1555.54    74.3 1547.02     104  1538.9   133.7 1524.27
   148.6 1520.19   163.4 1519.37   198.1 1519.46   272.4  1525.5   488.6 1527.69
   514.1 1523.42   529.1 1521.28   576.7 1527.79   625.7 1529.85   669.8 1549.42
   689.4 1551.98   699.3 1556.15   734.2  1558.4     769 1569.81   833.7 1585.09
   863.5 1596.07   893.4 1596.01   953.1 1617.01     973 1619.35   997.9 1626.26
  1032.7 1625.92  1057.6 1618.65  1077.5 1619.81  1157.1 1662.72  1186.9 1676.67
#Mann= 3 , 0 , 0
       0      .1       0   514.1    .045       0   529.1      .1       0
#XS Ineff= 2 , 0
          485.74 1527.55
Permanent Ineff=
       F       F
Bank Sta=514.1,529.1
XS Rating Curve= 0 ,0
Exp/Cntr=0.3,0.1

Type RM Length L Ch R = 1 ,123.5   ,92,123.5,158.5
XS GIS Cut Line= 6
     1860252.933      223125.858     1859995.242      223052.232
     1859891.268      223007.681     1859583.322       222981.73
     1859420.699      223114.943     1858922.644      223452.796
#Sta/Elev= 30
       0 1585.15    54.6 1544.45    84.4 1540.22   119.1  1518.9   158.8 1514.22
   307.4 1521.59   336.9 1525.64     426 1525.22   469.7    1519   484.7 1519.32
   515.7 1523.63   630.3 1527.51   655.3 1535.29   680.2 1550.11   699.9 1557.12
   734.2 1558.74   748.8 1566.23   787.9 1579.06     827 1580.62   880.8 1589.74
   915.3 1590.11     970  1582.3  1009.8    1586  1064.5 1605.27  1089.4 1606.15
  1104.3 1609.82  1208.8 1662.29  1273.4 1690.24    1348 1706.89  1502.2 1734.51
#Mann= 3 , 0 , 0
       0      .1       0   469.7    .045       0   484.7      .1       0
#XS Ineff= 2 , 0
          369.88 1525.73
Permanent Ineff=
       F       F
Bank Sta=469.7,484.7
XS Rating Curve= 0 ,0
Exp/Cntr=0.3,0.1

Chan Stop Cuts=-1
Use User Specified Reach Order=0